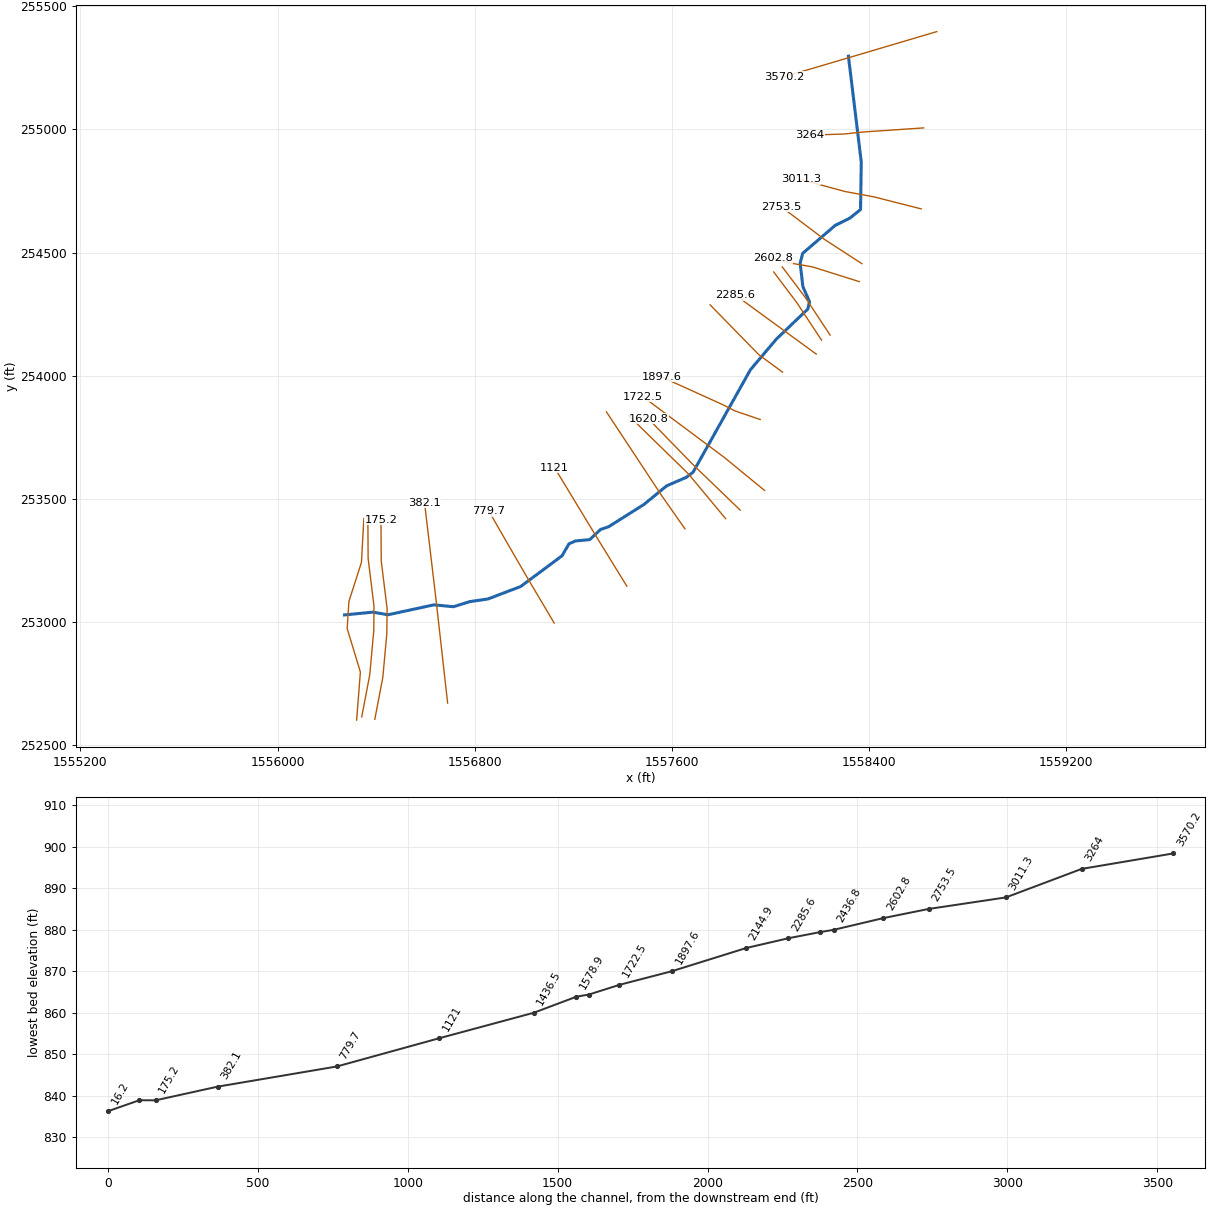
--- SLBCRT.prj (project) ---

Proj Title=SLBCRT
Current Plan=p01
Default Exp/Contr=0,0
English Units
Geom File=g01
Flow File=f01
Plan File=p01
BEGIN DESCRIPTION:
END DESCRIPTION:
DSS Export Rating Curves= 0
DSS Export Rating Curve Sorted= 0
DSS Export Volume Flow Curves= 0
DXF OffsetX= 0
DXF OffsetY= 0
DXF ScaleX= 0
DXF ScaleY= 0

--- SLBCRT.p01 (plan) ---

Plan Title=Floodplain
Program Version=4.00
Geom File=g01
Flow File=f01
K Sum by GR=0
Std Step Tol=0.01
Critical Tol=0.01
Num of Std Step Trials=20
Max Error Tol=0.3
Flow Tol Ratio=0.001
Split Flow NTrial=30
Split Flow Tol=0.02
Split Flow Ratio=0.02
Log Output Level=0
Friction Slope Method=1
Unsteady Friction Slope Method=2
Unsteady Bridges Friction Slope Method=1
Global Log Level=0
CheckData=False
Run HTab=0
Run UNet=0
Run PostProcess=0
UNET Theta=0
UNET Theta Warmup=0
UNET ZTol=0
UNET ZSATol=0
UNET MxIter=0
UNET MaxInSteps=0
UNET DtIC=0
UNET DtMin=0
UNET MaxCRTS=0
UNET WFStab=0
UNET SFStab=0
UNET WFX=0
UNET SFX=0
UNET DSS MLevel=0
UNET DZMax Abort=0
UNET Convert EG Bridges=0
UNET Use Existing IB Tables=0
UNET Froude Limit=0
UNET Froude Power=0
Write IC File=0
Echo Input=False
Echo Output=False
Write Detailed=0

--- SLBCRT.f01 (steady flow) ---

Flow Title=NFF Regression Equation
Program Version=4.10
Number of Profiles= 1
Profile Names=P100yr
River Rch & RM=SLBCRT,Main            ,3570.2
407.9536
Boundary for River Rch & Prof#=SLBCRT,Main            , 1
Up Type= 0
Dn Type= 3
Dn Slope=0.0164
DSS Import GetInterval= 0
DSS Import GetPeak= 0
DSS Import FillOption= 0

--- SLBCRT.g01 (geometry) ---

Geom Title=USGS 10m DEM
Program Version=4.10

River Reach=SLBCRT          ,Main
Reach XY= 30
     1558317.679      255297.451     1558369.844        254867.2
     1558366.985      254675.012     1558323.949      254639.865
     1558264.207      254610.429     1558132.147      254496.959
      1558121.73      254457.376     1558132.668      254362.584
     1558159.751      254300.084     1558152.974      254270.791
     1558024.797      254148.276     1557919.762      254024.144
     1557687.124      253608.345     1557659.346      253587.512
     1557579.485       253552.79     1557487.471      253477.269
     1557344.242      253386.991     1557311.256      253375.706
     1557267.679      253334.734     1557208.825      253329.005
     1557183.304      253317.547     1557154.658      253268.588
      1556986.95      253144.109     1556854.388      253093.793
     1556779.862      253082.694     1556714.033      253062.165
     1556634.867      253069.804     1556448.756      253029.526
     1556386.666      253040.119     1556272.101      253029.008

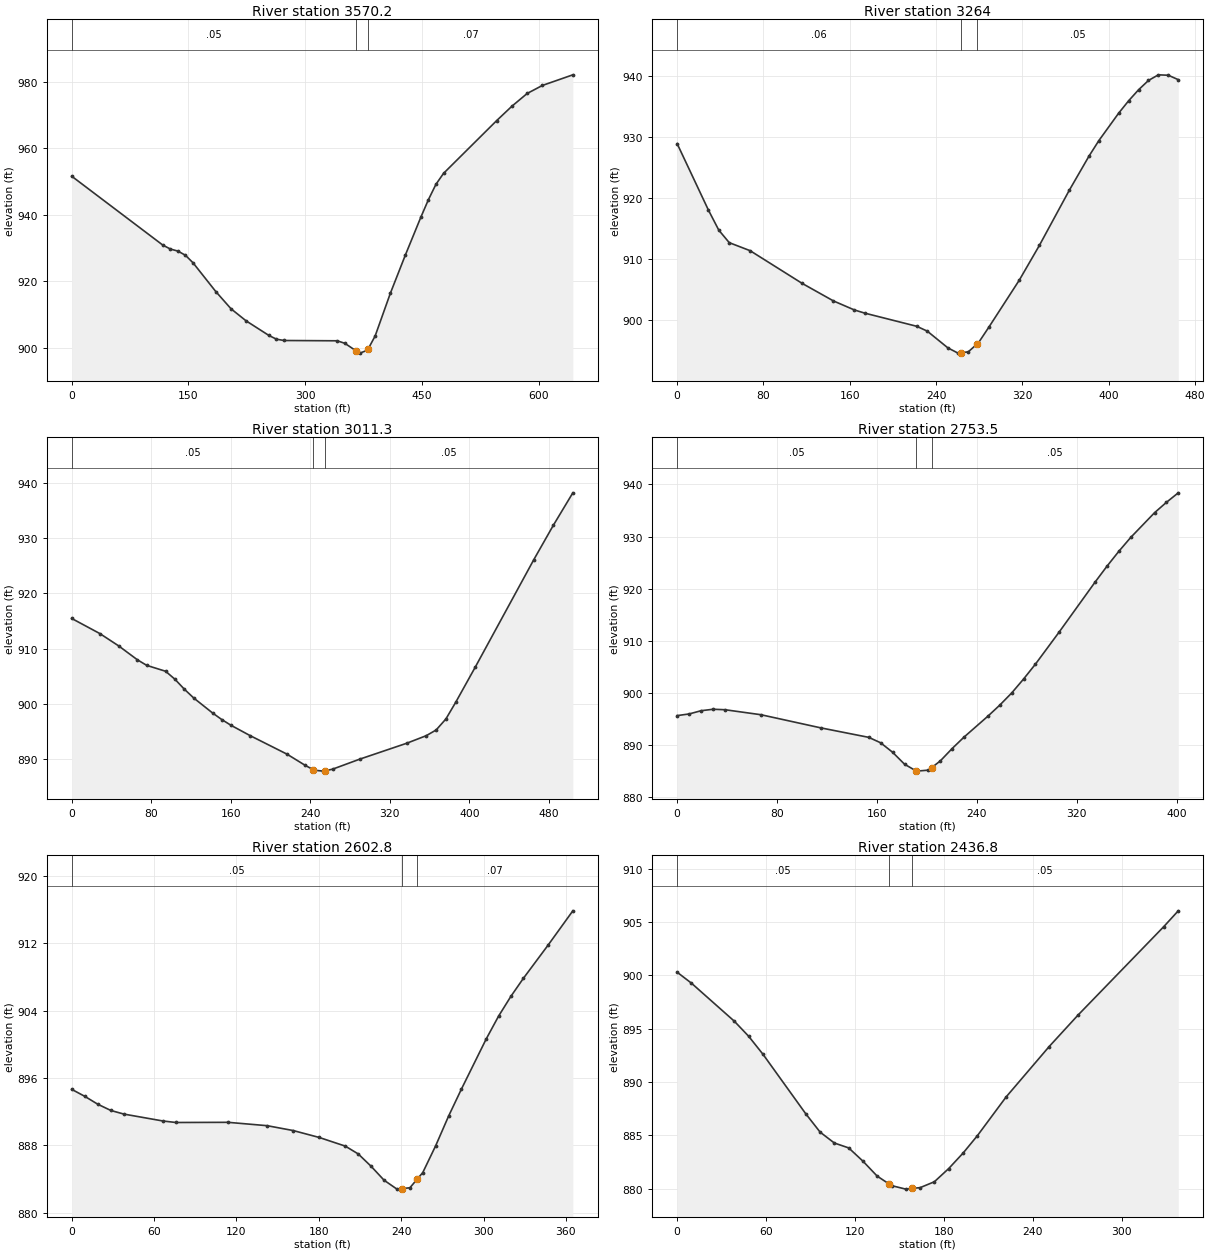
Type RM Length L Ch R = 1 ,3570.2  ,310.4,306.1,301.9
XS GIS Cut Line= 3
     1558676.426       255397.05     1558283.798      255280.716
     1558058.782      255214.436
#Sta/Elev= 30
       0  951.61     117   930.9   126.8   929.7   136.5  929.08   146.2  927.82
     156  925.54   185.2   916.9   204.8  911.71   224.2  908.08   253.5  903.69
   263.2  902.57     273  902.18   341.2  902.09     351  901.34     366  898.99
   370.5  898.38   380.2  899.28     381  899.63     390  903.54   409.5  916.36
     429  927.99   448.6   939.2   458.4  944.52   468.1  949.16   477.9  952.47
   546.3  968.37   565.9   972.7   585.4  976.51     605  978.93   644.1  982.12
#Mann= 3 , 0 , 0
       0     .05       0     366    .045       0     381     .07       0
Bank Sta=366,381
XS Rating Curve= 0 ,0
Exp/Cntr=0.3,0.1

Type RM Length L Ch R = 1 ,3264    ,259.3,252.7,246.4
XS GIS Cut Line= 4
     1558623.018      255006.103     1558382.132      254989.827
     1558297.497      254981.146     1558159.693      254976.806
#Sta/Elev= 30
       0  928.94      29  918.06    38.6  914.78    48.3  912.73    67.6  911.42
   115.9  906.06   144.9  903.19   164.2  901.72   173.8   901.2   222.1  899.04
   231.8  898.25   250.9  895.51   260.3  894.65   262.9  894.71   269.8  894.86
   277.9  896.13   279.2  896.33   288.7  898.85   317.1   906.6   335.7  912.28
   363.3  921.27   381.7   926.9   390.8  929.43   409.2  933.93   418.4  935.95
   427.6  937.75   436.8  939.28     446   940.2   455.2  940.13   464.4  939.41
#Mann= 3 , 0 , 0
       0     .06       0   262.9    .045       0   277.9     .05       0
Bank Sta=262.9,277.9
XS Rating Curve= 0 ,0
Exp/Cntr=0.3,0.1

Type RM Length L Ch R = 1 ,3011.3  ,267.5,257.8,247.1
XS GIS Cut Line= 4
     1558613.252      254677.327     1558421.195      254726.155
     1558304.007      254747.856     1558123.886      254796.684
#Sta/Elev= 30
       0  915.46    28.3  912.72    47.2  910.49    66.1  907.96    75.5  906.95
    94.4  905.89   103.8  904.44   113.2  902.65   122.7  901.04   141.6  898.33
     151  897.12   160.4  896.07   179.3  894.23   216.5  890.86   234.8  888.83
  242.66888.0687     244  887.94   253.2  887.78  255.04887.8525   262.3  888.13
   289.8  889.96     337  892.84   356.6  894.21   366.5  895.24   376.3  897.23
   386.1  900.23   405.8  906.62   464.7  926.11   484.3  932.33     504  938.24
#Mann= 3 , 0 , 0
       0     .05       0  242.66    .045       0  255.04     .05       0
Bank Sta=242.66,255.04
XS Rating Curve= 0 ,0
Exp/Cntr=0.3,0.1

Type RM Length L Ch R = 1 ,2753.5  ,140.8,150.7,161.1
XS GIS Cut Line= 3
     1558372.367      254454.888     1558219.628      254554.042
     1558044.676      254686.007
#Sta/Elev= 30
       0  895.65     9.6  895.97    19.2  896.59    28.8  896.87    38.3  896.78
    67.1  895.82     115   893.3   153.4  891.48   162.9  890.44   172.5  888.62
   182.1  886.32   191.6     885   201.2  885.19   203.9  885.69   210.7  886.96
   220.2  889.34   229.7  891.53   248.8  895.54   258.3  897.66   267.8  899.98
   277.4  902.68   286.9  905.54     306  911.73   334.6  921.26   344.1   924.3
   353.6  927.16   363.1  929.82   382.2  934.57   391.7  936.56   401.2  938.39
#Mann= 3 , 0 , 0
       0     .05       0   191.6    .045       0   203.9     .05       0
Bank Sta=191.6,203.9
XS Rating Curve= 0 ,0
Exp/Cntr=0.3,0.1

Type RM Length L Ch R = 1 ,2602.8  ,186.7,166,94.5
XS GIS Cut Line= 4
     1558361.617      254382.072     1558171.513      254441.968
      1558088.18      254456.291     1558009.838      254477.341
#Sta/Elev= 29
       0  894.66     9.5  893.83      19  892.89    28.5  892.15      38  891.72
    66.4   890.9    75.9  890.72   113.9  890.74   142.4  890.34   161.4  889.76
   180.3  888.94   199.3  887.91   208.7  886.98   218.1  885.51   227.5  883.86
   236.9   882.8   240.9  882.87   246.3  882.96  251.61883.9825   255.7  884.77
   265.1  887.96   274.5  891.48   283.9  894.71   301.9  900.65   310.9  903.36
   319.9  905.72   328.9  907.84     347  911.81     365  915.88
#Mann= 3 , 0 , 0
       0     .05       0   240.9    .045       0  251.61     .07       0
Bank Sta=240.9,251.61
XS Rating Curve= 0 ,0
Exp/Cntr=0.3,0.1

Type RM Length L Ch R = 1 ,2436.8  ,42.7,45.4,97.7
XS GIS Cut Line= 3
     1558243.243      254165.174     1558142.332      254318.169
     1558049.016      254441.867
#Sta/Elev= 25
       0  900.29     9.6  899.27    38.6   895.7    48.2   894.3    57.9  892.61
    86.8  887.03    96.5  885.31   106.1  884.29   115.8  883.83   125.4  882.59
     135  881.19   143.3  880.43   144.7   880.3   154.3  879.97   158.3  880.03
     164  880.11   173.6  880.66   183.3   881.9     193  883.35   202.6  884.97
     222   888.6   251.1  893.33   270.4  896.25   328.5  904.57   338.2  906.04
#Mann= 3 , 0 , 0
       0     .05       0   143.3    .045       0   158.3     .05       0
Bank Sta=143.3,158.3
XS Rating Curve= 0 ,0
Exp/Cntr=0.3,0.1

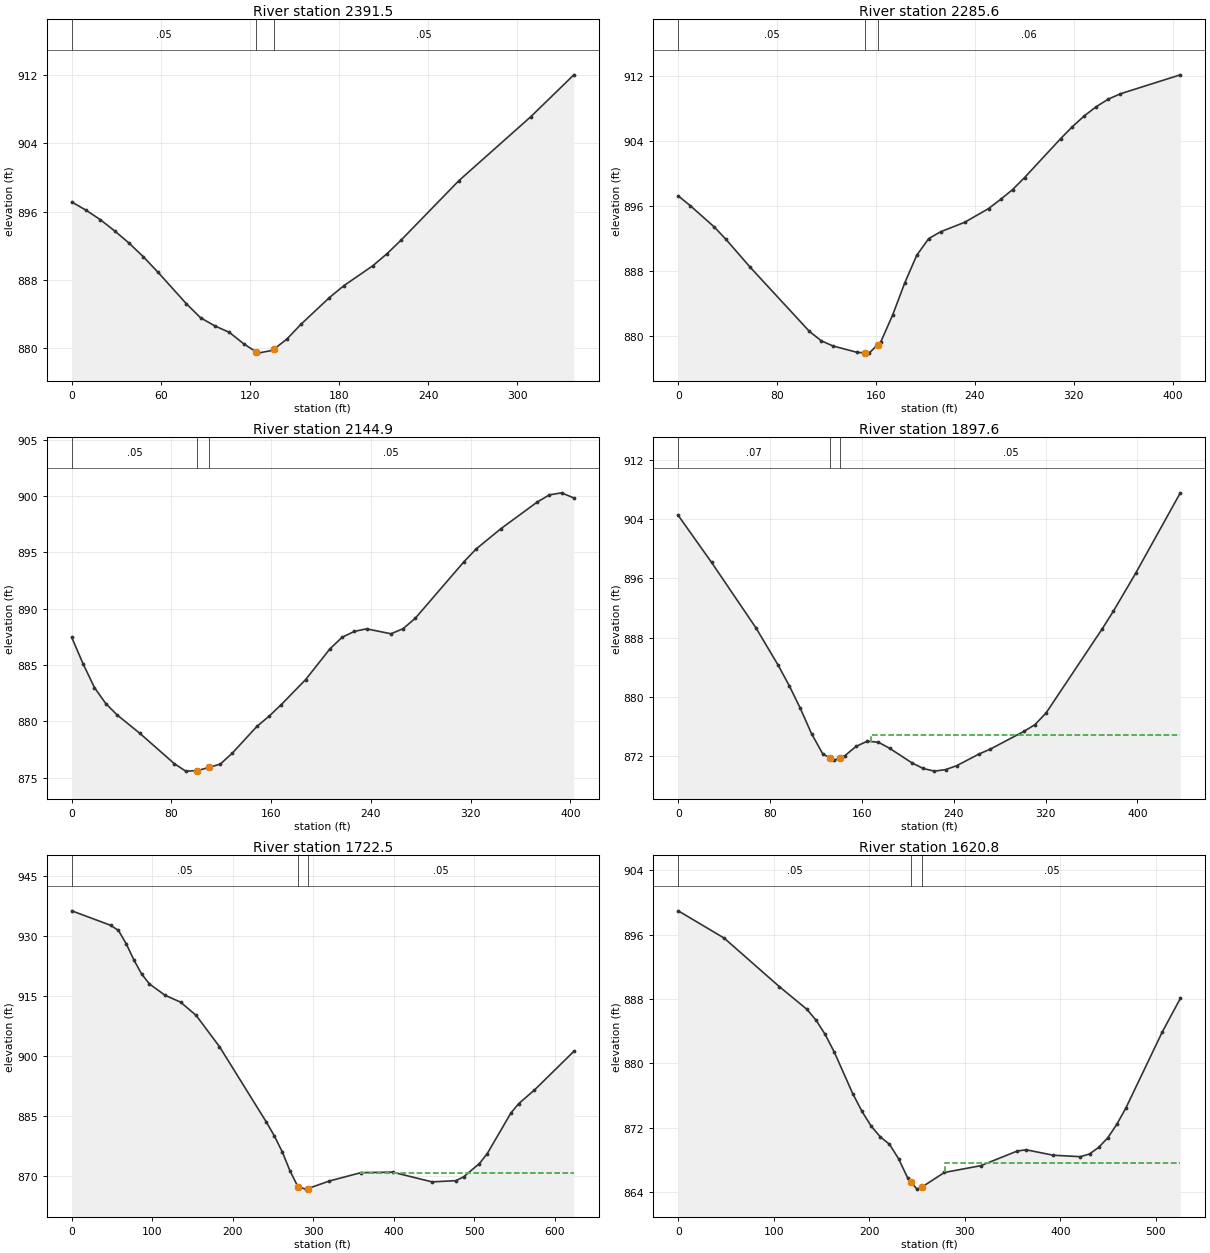
Type RM Length L Ch R = 1 ,2391.5  ,97.7,105.9,114
XS GIS Cut Line= 3
     1558208.521      254144.558      1558107.61      254297.553
     1558014.294       254421.25
#Sta/Elev= 26
       0  897.14     9.6  896.18    19.3  895.06    28.9  893.75    38.6  892.32
    48.2  890.72    57.9  888.94    77.2  885.21    86.8  883.56    96.5   882.6
   106.1  881.86   115.8  880.52  124.12879.5693   125.4  879.42     135  879.74
   136.3879.9133   144.7  881.03   154.3  882.79   173.6  885.94   183.3  887.33
   202.6  889.64   212.3  891.07     222   892.7   260.8  899.65   309.2  907.14
   338.2  912.05
#Mann= 3 , 0 , 0
       0     .05       0  124.12    .045       0   136.3     .05       0
Bank Sta=124.12,136.3
XS Rating Curve= 0 ,0
Exp/Cntr=0.3,0.1

Type RM Length L Ch R = 1 ,2285.6  ,140.8,140.8,139.4
XS GIS Cut Line= 3
     1558187.138      254087.801     1558046.846      254190.131
     1557859.013      254327.385
#Sta/Elev= 30
       0  897.26     9.6  896.08    28.9  893.48    38.6  891.93    57.9  888.55
   106.1  880.62   115.8  879.45   125.4  878.81   144.7  878.04  150.93877.9785
   154.4  877.94   161.4878.9681     164  879.35   173.6  882.66   183.3  886.57
     193  889.96   202.7  892.02   212.4  892.86   231.8  894.02   251.2  895.71
   260.9  896.84   270.6  898.04   280.3  899.52   309.4  904.29     319  905.77
   328.7  907.11   338.4  908.24   348.1  909.16   357.8  909.81   406.3  912.14
#Mann= 3 , 0 , 0
       0     .05       0  150.93    .045       0   161.4     .06       0
Bank Sta=150.93,161.4
XS Rating Curve= 0 ,0
Exp/Cntr=0.3,0.1

Type RM Length L Ch R = 1 ,2144.9  ,243.6,247.2,252.1
XS GIS Cut Line= 4
     1558050.419      254014.494     1557999.103      254052.327
     1557954.381      254084.959     1557756.047      254287.787
#Sta/Elev= 30
       0  887.45     9.1  885.11    18.2     883    27.3  881.58    36.4  880.57
    54.6  878.94    82.2  876.25    91.4  875.58   100.7  875.62   109.9  875.91
   119.1   876.2   128.9  877.19   148.5  879.55   158.2  880.45     168  881.48
   187.6  883.71   207.2  886.45   216.9  887.47   226.7  887.99   236.5  888.22
   256.1  887.78   265.8  888.23   275.6  889.16   314.8   894.2   324.5  895.32
   344.1   897.1   373.4  899.48   383.2  900.12     393   900.3   402.8  899.84
#Mann= 3 , 0 , 0
       0     .05       0   100.7    .045       0   109.9     .05       0
Bank Sta=100.7,109.9
XS Rating Curve= 0 ,0
Exp/Cntr=0.3,0.1

Type RM Length L Ch R = 1 ,1897.6  ,179,175.1,171.3
XS GIS Cut Line= 4
     1557959.534       253822.22     1557858.839      253856.508
     1557806.902      253882.807     1557558.492      253995.397
#Sta/Elev= 30
       0   904.5      29  898.17    67.7  889.33      87  884.31    96.7  881.53
   106.4  878.46   116.1  875.06   125.8  872.36  132.07871.7809   135.5  871.46
  141.27871.8403   145.2   872.1   154.9  873.35   164.6  874.04   174.3  873.91
   184.1  873.09   203.6  871.12   213.3  870.37     223  870.01   232.8  870.21
   242.5  870.74     262  872.32   271.7  872.97     301  875.36   310.7  876.28
   320.4  877.86   369.1  889.16   378.9  891.56   398.4   896.7   437.3  907.55
#Mann= 3 , 0 , 0
       0     .07       0  132.07    .045       0  141.27     .05       0
#XS Ineff= 2 , 0
                          168.06          874.95
Permanent Ineff=
       F       F
Bank Sta=132.07,141.27
XS Rating Curve= 0 ,0
Exp/Cntr=0.3,0.1

Type RM Length L Ch R = 1 ,1722.5  ,104.9,101.7,98.7
XS GIS Cut Line= 3
     1557977.184      253534.315     1557812.799      253669.043
     1557483.008      253915.146
#Sta/Elev= 30
       0  936.35    48.3  932.73      58  931.44    67.6  928.14    77.3  924.02
      87  920.49    96.6  918.05   115.9  915.23   135.2  913.51   154.6  910.18
   183.6  902.37   241.9  883.48   251.7  880.06   261.5   876.1   271.3  871.25
   281.1  867.31   290.9  866.72  293.35866.8566   320.3  868.76   359.5  870.85
   398.7  870.97   447.7  868.54   477.1  868.83   486.9  869.78   506.5  873.09
   516.3  875.58   545.7  885.74   555.5  888.12     575  891.51     624  901.19
#Mann= 3 , 0 , 0
       0     .05       0   281.1    .045       0  293.35     .05       0
#XS Ineff= 2 , 0
                          358.41          870.86
Permanent Ineff=
       F       F
Bank Sta=281.1,293.35
XS Rating Curve= 0 ,0
Exp/Cntr=0.3,0.1

Type RM Length L Ch R = 1 ,1620.8  ,43.8,41.9,41
XS GIS Cut Line= 3
     1557878.226      253454.454     1557691.308      253634.532
     1557505.613      253824.969
#Sta/Elev= 30
       0  898.95    48.1  895.56   105.7  889.55   134.6  886.73   144.2  885.38
   153.8   883.6   163.4  881.39   182.6  876.26   192.3  874.05   201.9  872.22
   211.5  870.88   221.1  869.96   230.7  868.15   240.3  865.74     244  865.22
   249.9  864.39  255.49864.6849   278.6  866.46   316.6   867.3   354.6  869.11
     364  869.28   392.5   868.6     421  868.42   430.5  868.76     440  869.57
   449.5  870.75     459  872.43   468.5  874.46   506.5  883.88   525.5  888.07
#Mann= 3 , 0 , 0
       0     .05       0     244    .045       0  255.49     .05       0
#XS Ineff= 2 , 0
                          278.93          867.64
Permanent Ineff=
       F       F
Bank Sta=244,255.49
XS Rating Curve= 0 ,0
Exp/Cntr=0.3,0.1

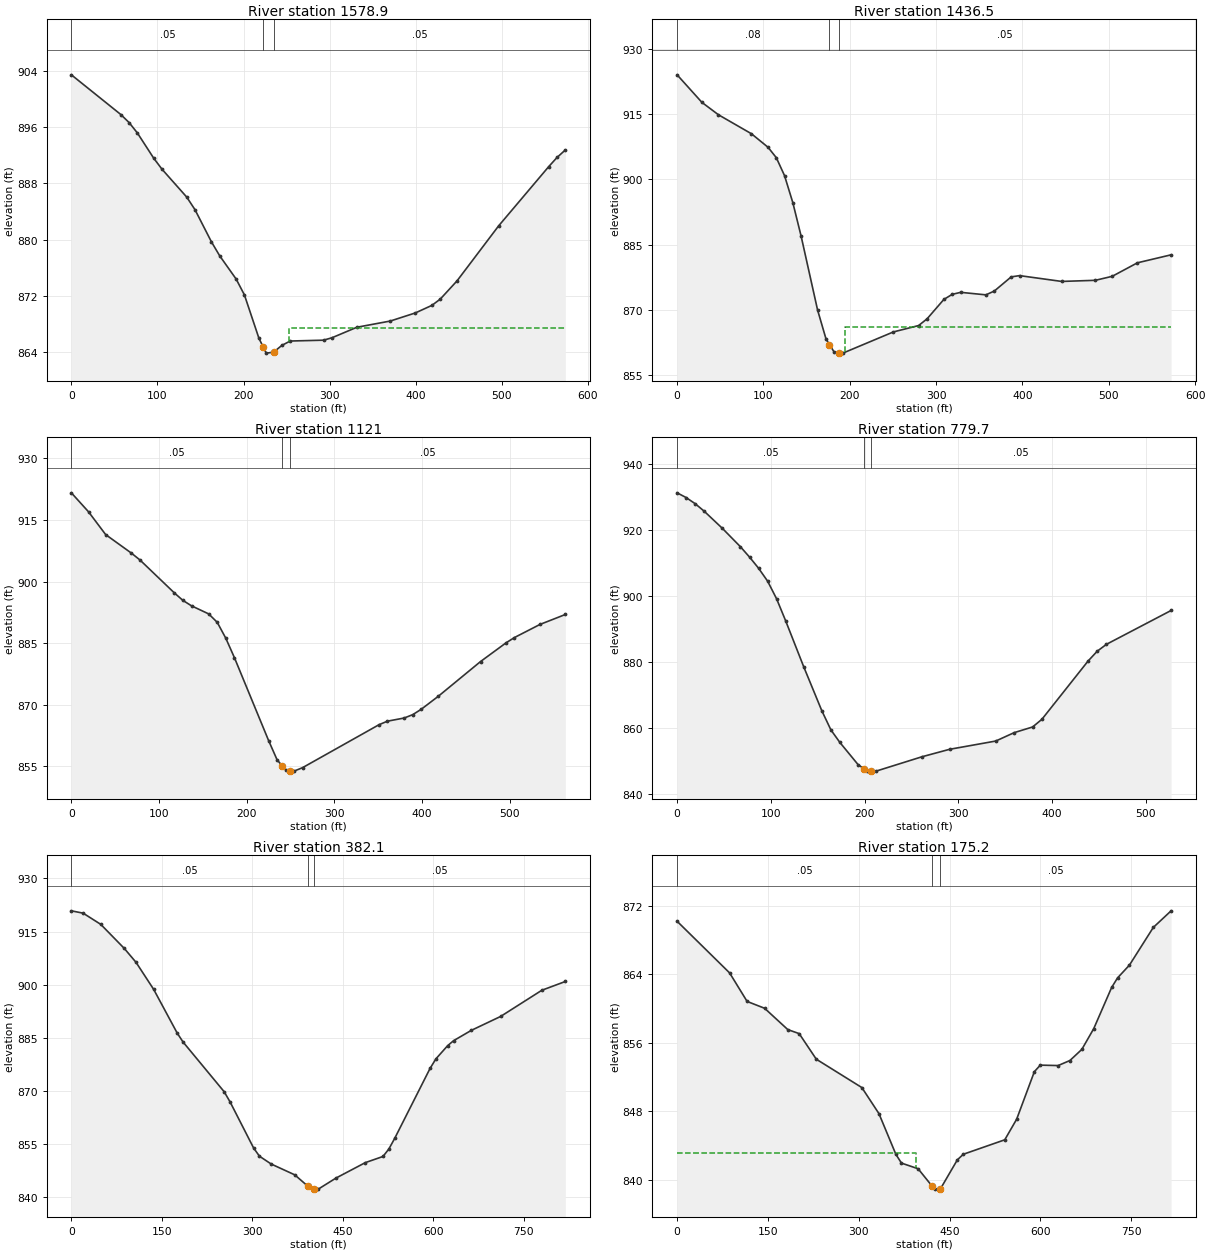
Type RM Length L Ch R = 1 ,1578.9  ,144.7,142.4,138
XS GIS Cut Line= 4
     1557819.198      253419.731     1557690.719      253574.274
     1557669.152      253600.381      1557426.62      253837.121
#Sta/Elev= 30
       0  903.42    57.4  897.78      67  896.64    76.6  895.17    95.7  891.56
   105.3     890     134  886.04   143.6  884.25   162.7  879.68   172.3  877.69
   191.4  874.39     201  872.14   217.9  865.96   222.9  864.72   226.4  863.86
   234.8  863.99   244.5  864.96   254.2  865.58   292.9   865.7   302.6  866.04
   331.7  867.54   370.4  868.42   399.5  869.57   418.8  870.65   428.5  871.54
   447.9  874.12   496.3  881.95   554.4  890.36   564.1  891.67   573.8  892.74
#Mann= 3 , 0 , 0
       0     .05       0   222.9    .045       0   234.8     .05       0
#XS Ineff= 2 , 0
                          252.84          867.48
Permanent Ineff=
       F       F
Bank Sta=222.9,234.8
XS Rating Curve= 0 ,0
Exp/Cntr=0.3,0.1

Type RM Length L Ch R = 1 ,1436.5  ,317.2,315.5,313.8
XS GIS Cut Line= 3
     1557654.268      253378.065     1557560.879      253511.314
     1557335.411      253853.154
#Sta/Elev= 30
       0  924.08    28.7  917.74    47.9  914.88    86.1  910.51   105.3   907.4
   114.9     905   124.4  900.88     134  894.67   143.6  886.97   162.7  869.93
   172.5  863.24  176.51861.9597   182.2  860.14   187.6  860.06     192  859.99
   250.5  864.87   279.7  866.34   289.5  867.88     309  872.36   318.7  873.53
   328.5  873.99   357.7  873.41   367.5   874.3     387  877.55   396.7  877.84
   445.5   876.5   484.5  876.76     504  877.68   533.2  880.79   572.2  882.63
#Mann= 3 , 0 , 0
       0     .08       0  176.51    .045       0   187.6     .05       0
#XS Ineff= 2 , 0
                          194.82          866.05
Permanent Ineff=
       F       F
Bank Sta=176.51,187.6
XS Rating Curve= 0 ,0
Exp/Cntr=0.3,0.1

Type RM Length L Ch R = 1 ,1121    ,340.5,341.3,342.1
XS GIS Cut Line= 3
     1557418.157      253145.426     1557305.325      253328.747
     1557124.754      253626.329
#Sta/Elev= 30
       0  921.63    19.6     917    39.1  911.46    68.5  906.94    78.3  905.26
   117.4  897.26   127.2  895.43     137  894.11   156.6  892.14   166.3   890.1
   176.1  886.22   185.9   881.5   224.9   861.3   234.6   856.6  240.71 855.075
   244.3  854.18   249.6 854.001   253.9  853.85   263.6  854.69   350.6  865.13
   360.3  866.01   379.6  866.79   389.3  867.61     399  868.92   418.3  872.06
   466.6  880.54   495.7   885.1   505.3  886.39   534.3  889.57   563.3     892
#Mann= 3 , 0 , 0
       0     .05       0  240.71    .045       0   249.6     .05       0
Bank Sta=240.71,249.6
XS Rating Curve= 0 ,0
Exp/Cntr=0.3,0.1

Type RM Length L Ch R = 1 ,779.7   ,406.5,397.6,388.2
XS GIS Cut Line= 3
     1557123.018       252996.12     1557005.071      253195.331
     1556857.393      253450.981
#Sta/Elev= 30
       0  931.33     9.6   929.9    19.3  928.03    28.9  925.76    48.2  920.59
    67.5  915.01    77.2  911.88    86.8  908.52    96.5  904.59   106.1  899.23
   115.8  892.54     135  878.66   154.3  865.35     164  859.54   173.6  855.73
   192.9  849.05  199.32847.7446   202.6  847.08  206.81847.0686   212.2  847.05
     261  851.39   290.6  853.66   339.8  856.16   359.4   858.7   379.1  860.42
     389  862.74   438.2  880.37     448  883.36   457.9  885.46   526.8   895.7
#Mann= 3 , 0 , 0
       0     .05       0  199.32    .045       0  206.81     .05       0
Bank Sta=199.32,206.81
XS Rating Curve= 0 ,0
Exp/Cntr=0.3,0.1

Type RM Length L Ch R = 1 ,382.1   ,209.7,207,203.7
XS GIS Cut Line= 3
     1556690.546      252671.217     1556644.946      253078.069
     1556596.737      253484.898
#Sta/Elev= 30
       0  920.85    19.5  920.19    48.7  917.03    87.7  910.23   107.2   906.3
   136.5  898.64   175.5  886.29   185.2  883.77   253.4  869.71   263.2  866.83
   302.2  853.81   311.9  851.49   331.4  849.28   370.4  846.23  392.55842.9547
  403.11842.2043   409.4  842.19   438.7  845.31   487.4  849.68   516.7  851.42
   526.4  853.52   536.2  856.56   594.7  876.29   604.5  879.02     624  882.75
   633.8  884.15     663  887.05   711.8     891   780.1   898.4   819.1  900.88
#Mann= 3 , 0 , 0
       0     .05       0  392.55    .045       0  403.11     .05       0
Bank Sta=392.55,403.11
XS Rating Curve= 0 ,0
Exp/Cntr=0.3,0.1

Type RM Length L Ch R = 1 ,175.2   ,54,54,54
XS GIS Cut Line= 6
     1556394.936      252605.134     1556427.488      252775.489
     1556443.764      252953.441     1556444.849      253054.352
     1556420.978       253248.58     1556419.893       253415.68
#Sta/Elev= 30
       0  870.18    86.7  864.15   115.6  860.82   144.5  860.02   182.8  857.53
   201.6  857.06   229.9  854.07   305.1  850.76   333.3  847.72   361.3  842.96
   370.5  841.94     398  841.28     421  839.26   425.5   838.9   434.7  838.91
   462.8  842.32   472.6  842.97   541.1  844.66   560.7  847.06     590  852.62
   599.8  853.38   629.2  853.33   648.7  853.92   668.4  855.22   688.1  857.65
   717.6  862.45   727.4  863.57     747  865.06   786.4  869.46   815.8   871.4
#Mann= 3 , 0 , 0
       0     .05       0     421    .045       0   434.7     .05       0
#XS Ineff= 2 , 0
          394.65  843.07
Permanent Ineff=
       F       F
Bank Sta=421,434.7
XS Rating Curve= 0 ,0
Exp/Cntr=0.3,0.1

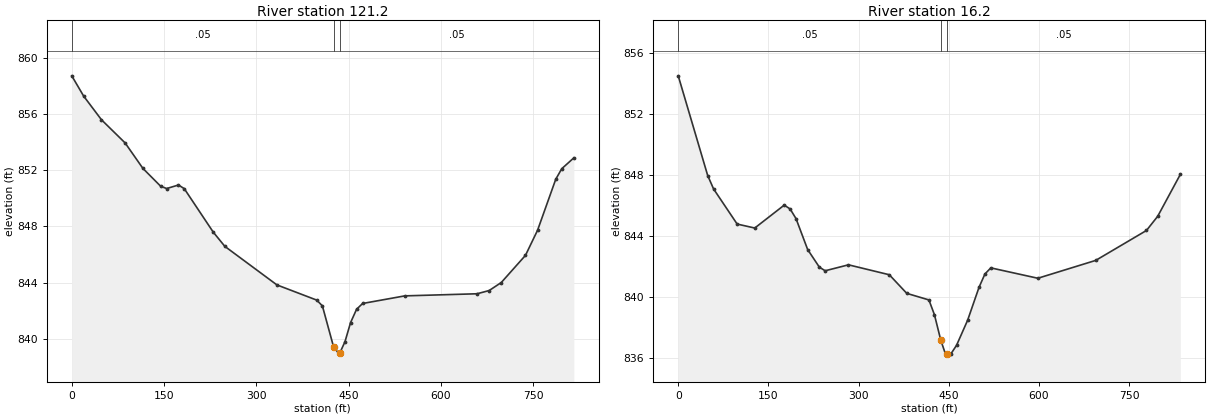
Type RM Length L Ch R = 1 ,121.2   ,106.9,104.9,103.7
XS GIS Cut Line= 6
     1556341.768      252614.899      1556374.32      252785.255
     1556390.596      252963.206     1556391.681      253064.118
     1556367.809      253258.345     1556366.724      253425.446
#Sta/Elev= 30
       0   858.7    19.3  857.26    48.2  855.58    86.7  853.93   115.6  852.12
   144.5  850.85   154.2  850.69   173.4  850.94   182.8  850.68   229.9  847.59
   248.7  846.58   333.3  843.84     398  842.76   407.2  842.35   425.5  839.42
   434.7  838.92   435.6  839.01   443.9   839.8     453  841.16   462.8  842.11
   472.6  842.52   541.1  843.06   658.6  843.21   678.2  843.44   697.9  844.01
   737.2  845.94   756.9  847.73   786.4  851.35   796.2   852.1   815.8  852.87
#Mann= 3 , 0 , 0
       0     .05       0   425.5    .045       0   435.6     .05       0
Bank Sta=425.5,435.6
XS Rating Curve= 0 ,0
Exp/Cntr=0.3,0.1

Type RM Length L Ch R = 1 ,16.2    ,4.3,16.2,26.8
XS GIS Cut Line= 6
     1556321.151      252601.878     1556336.342      252797.191
     1556282.754      252973.565     1556289.786      253083.722
     1556340.683      253242.069     1556350.448      253420.021
#Sta/Elev= 30
       0   854.5      49  847.97    58.8  847.09      98  844.79   127.3  844.53
   176.3  846.03   186.1  845.78   195.9  845.15   215.3  843.12   234.7  841.97
   244.4  841.73   283.2  842.12   351.1  841.47   380.2  840.25     417  839.82
   426.2  838.85  436.71837.1877   444.6  836.27     447836.2794   453.8   836.3
     463  836.85   481.4  838.49   500.4  840.65   510.2  841.52     520  841.92
   598.2  841.24   694.5  842.41   778.9  844.37   797.6   845.3   835.2  848.04
#Mann= 3 , 0 , 0
       0     .05       0  436.71    .045       0     447     .05       0
Bank Sta=436.71,447
XS Rating Curve= 0 ,0
Exp/Cntr=0.3,0.1

Chan Stop Cuts=-1
Use User Specified Reach Order=0
Composite Channel Slope=5